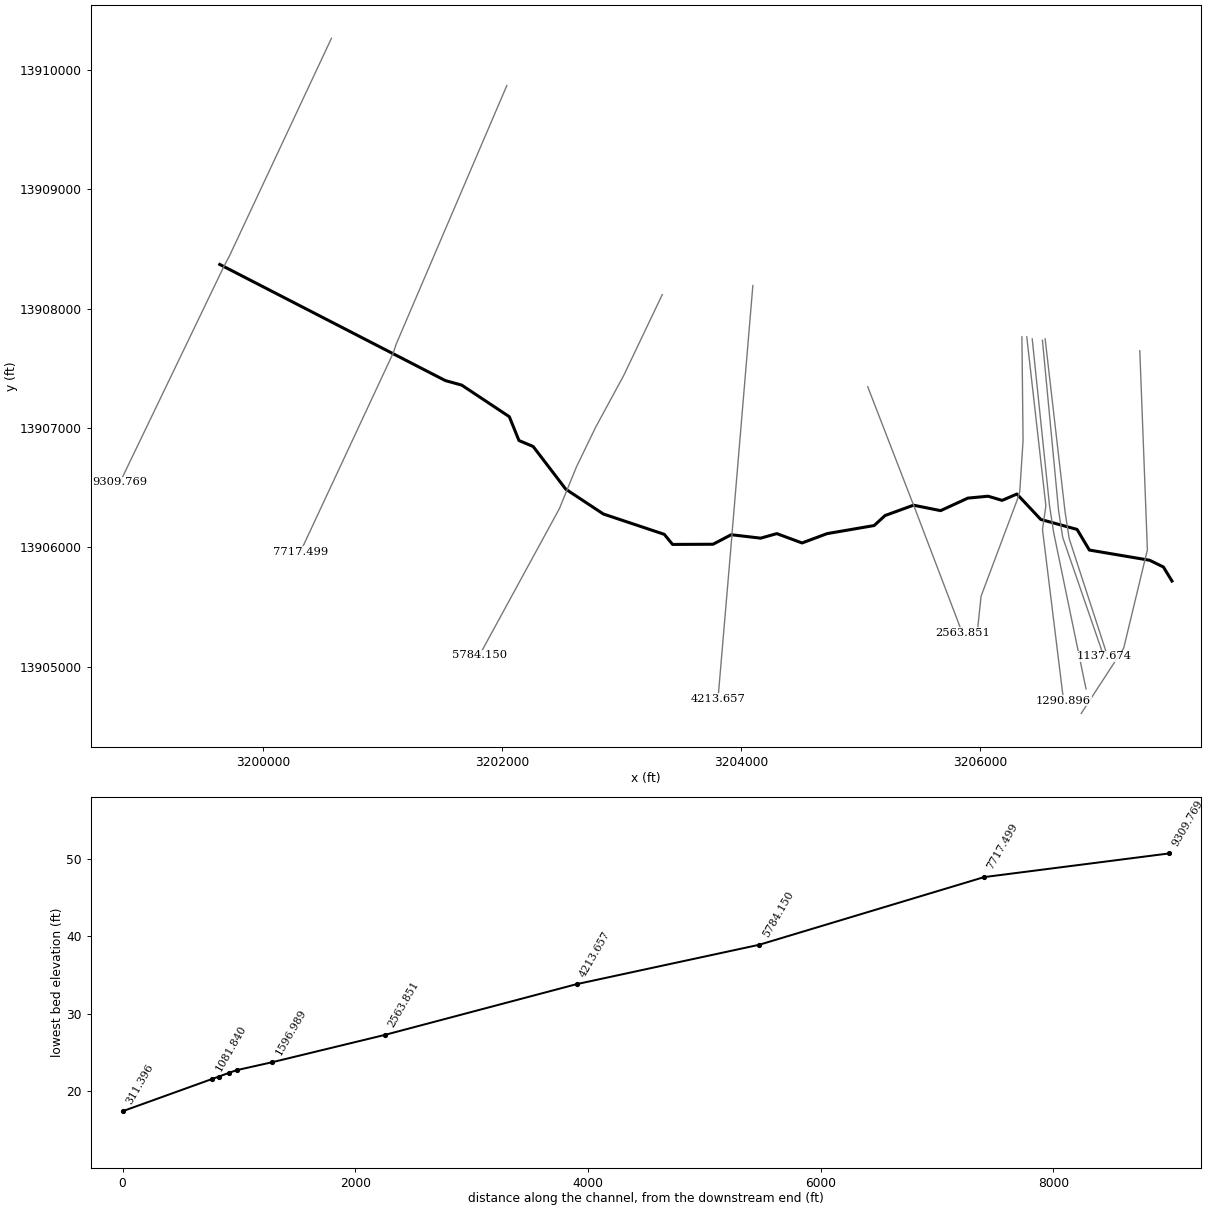
--- R102-13-00.prj (project) ---

Proj Title=R102-13-00
Current Plan=p02
Default Exp/Contr=.3,.1
English Units
Geom File=g02
Flow File=f01
Flow File=f02
Plan File=p04
Plan File=p02
Y Axis Title=Elevation
X Axis Title(PF)=Main Channel Distance
X Axis Title(XS)=Station
BEGIN DESCRIPTION:
Jackson Bayou Watershed
Tributary 3.08 to Gum Gully
HCFCD Unit R102-13-00
(Flood Hazard) Model
10, 2, 1, 0.2% Event
Filename r1021300.prj
Prepared by:  FTN Associates Ltd.   DATE:  May 2003
Reviewed by:____________   DATE: ________________
STATUS (FINAL RAS)
Starting condition is normal depth, channel slope = 0.00492 computed from RS 311.396 (444v1) @ 17.43 ft and RS 1596.989 (444v2) @ 23.76 ft.
END DESCRIPTION:
DSS Export Rating Curves= 0
DSS Export Rating Curve Sorted= 0
DSS Export Volume Flow Curves= 0
DXF OffsetX= 0
DXF OffsetY= 0
DXF ScaleX= 1
DXF ScaleY= 10

--- R102-13-00.p02 (plan) ---

Plan Title=Floodway
Version=Version 3.0.1  Mar 2001
Short Identifier=Floodway0607
Geom File=g02
Flow File=f02
Subcritical Flow
K Sum by GR= 0
Std Step Tol= 0.01
Critical Tol= 0.01
Num of Std Step Trials= 20
Max Error Tol= 0.3
Flow Tol Ratio= 0.001
Split Flow NTrial= 30
Split Flow Tol= 0.02
Split Flow Ratio= 0.02
Log Output Level= 0
Friction Slope Method= 1
Unsteady Friction Slope Method= 2
Parabolic Critical Depth
Global Vel Dist= 0 , 0 , 0
Global Log Level= 0
CheckData=True
Encroach Param=-1 ,0,0, 2
Encroach River=R102-13-00
Encroach Reach=Gum Gully 3.08
Encroach Node=9309.769
       1    2000    2240
Encroach Node=7717.499
       1  2285.9 2474.01
Encroach Node=5784.150
       1    1780    1850
Encroach Node=4213.657
       1 2067.84    2113
Encroach Node=2563.851
       1    1040    1095
Encroach Node=1596.989
       1    1296 1375.87
Encroach Node=1290.896
       1    1485    1580
Encroach Node=1225.451
       1 1488.85  1572.5
Encroach Node=1181
       1 1488.85  1583.5
Encroach Node=1137.674
       1 1499.85  1583.5
Encroach Node=1081.840
       1 1527.71 1611.36
Encroach Node=311.396
       1 1707.03 1786.92
Encroach Reach=R102-13-00_0003
Encroach Node=9309.769
       1    2000    2240
Encroach Node=7717.499
       1  2285.9 2474.01
Encroach Node=5784.150
       1    1780    1850
Encroach Node=4213.657
       1 2067.84    2113
Encroach Node=2563.851
       1    1040    1095
Encroach Node=1596.989
       1    1296 1375.87
Encroach Node=1290.896
       1    1485    1580
Encroach Node=1225.451
       1 1488.85  1572.5
Encroach Node=1181
       1 1488.85  1583.5
Encroach Node=1137.674
       1 1499.85  1583.5
Encroach Node=1081.840
       1 1527.71 1611.36
Encroach Node=311.396
       1 1707.03 1786.92
Computation Interval=1HOUR
Output Interval=1HOUR
Run HTab= 0
Run UNet= 0
Run PostProcess= 0
UNET Theta= 1
UNET ZTol= 0.02
UNET ZSATol= 0.1
UNET MxIter= 20
UNET MaxInSteps= 20
UNET DtIC= 0
UNET DtMin= 0
UNET MaxCRTS= 20
UNET WFStab= 2
UNET SFStab= 1
UNET WFX= 1
UNET SFX= 1
UNET Convert EG Bridges=-1
UNET Use Existing IB Tables=-1
Instantaneous Interval=1HOUR
Write IC File= 0
Write Velocity= 0
Write Detailed= 0

--- R102-13-00.p04 (plan) ---

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Plan Title=FEMA Effective June 2007
Short Identifier=FEMAeff0607
Geom File=g02
Flow File=f01
Encroach Param=-1 ,0,0, 0

--- R102-13-00.f02 (steady flow) ---

Flow Title=Floodway
Version=Version 3.0.1  Mar 2001
Number of Profiles= 2
Profile Names=1PCT_100yr,1PCTFloodway_100yrFW
River Rch & RM=R102-13-00,R102-13-00_0003 ,9309.769
     915     915
River Rch & RM=R102-13-00,R102-13-00_0003 ,7717.499
    1152    1152
River Rch & RM=R102-13-00,R102-13-00_0003 ,5784.150
    1435    1435
River Rch & RM=R102-13-00,R102-13-00_0003 ,4213.657
    1807    1807
River Rch & RM=R102-13-00,R102-13-00_0003 ,2563.851
    2068    2068
River Rch & RM=R102-13-00,R102-13-00_0003 ,1596.989
    2158    2158
River Rch & RM=R102-13-00,R102-13-00_0003 ,1290.896
    2222    2222
River Rch & RM=R102-13-00,R102-13-00_0003 ,1081.840
    2475    2475
Boundary for River Rch & Prof#=R102-13-00,R102-13-00_0003 , 1
Up Type= 0
Dn Type= 3
Dn Slope=.00492
DSS Import GetInterval= 0
DSS Import GetPeak= 0
DSS Import FillOption= 0

--- R102-13-00.f01 (steady flow) ---

Flow Title=FEMA Effective June 2007
Version=Version 3.0.1  Mar 2001
Number of Profiles= 4
Profile Names=10PCT_10yr,2PCT_50yr,1PCT_100yr,0.2PCT_500yr
River Rch & RM=R102-13-00,R102-13-00_0003 ,9309.769
     537     786     915    1280
River Rch & RM=R102-13-00,R102-13-00_0003 ,7717.499
     676     989    1152    1611
River Rch & RM=R102-13-00,R102-13-00_0003 ,5784.150
     839    1231    1435    2012
River Rch & RM=R102-13-00,R102-13-00_0003 ,4213.657
    1053    1549    1807    2541
River Rch & RM=R102-13-00,R102-13-00_0003 ,2563.851
    1203    1773    2068    2914
River Rch & RM=R102-13-00,R102-13-00_0003 ,1596.989
    1254    1850    2158    3043
River Rch & RM=R102-13-00,R102-13-00_0003 ,1290.896
    1291    1905    2222    3135
River Rch & RM=R102-13-00,R102-13-00_0003 ,1081.840
    1435    2121    2475    3496
Boundary for River Rch & Prof#=R102-13-00,R102-13-00_0003 , 1
Up Type= 0
Dn Type= 3
Dn Slope=.00492
DSS Import GetInterval= 0
DSS Import GetPeak= 0
DSS Import FillOption= 0

--- R102-13-00.g02 (geometry) ---

Geom Title=R102-13-00 June 2007
Version=Version 3.0.1  Mar 2001

River Reach=R102-13-00      ,R102-13-00_0003
Reach XY= 30
     3199634.052    13908369.461     3201522.276    13907397.133
     3201660.297    13907358.793     3202059.026    13907094.253
     3202139.538    13906894.888      3202258.39    13906845.047
     3202531.421    13906487.644     3202846.501    13906279.509
     3203356.732    13906109.178     3203425.929    13906024.773
     3203765.069    13906026.294      3203917.15    13906106.137
     3204163.521    13906077.241     3204298.873    13906115.262
     3204510.265     13906036.94     3204720.137    13906115.262
     3205114.026    13906182.938     3205205.275    13906266.582
     3205443.281    13906353.268     3205670.642    13906307.644
     3205898.763     13906412.58     3206068.333    13906428.548
     3206185.435    13906393.569     3206309.381    13906446.798
     3206509.368    13906233.885     3206813.417    13906150.278
     3206916.184    13905977.628     3207420.905    13905892.252
      3207536.14    13905835.887     3207608.029    13905718.219

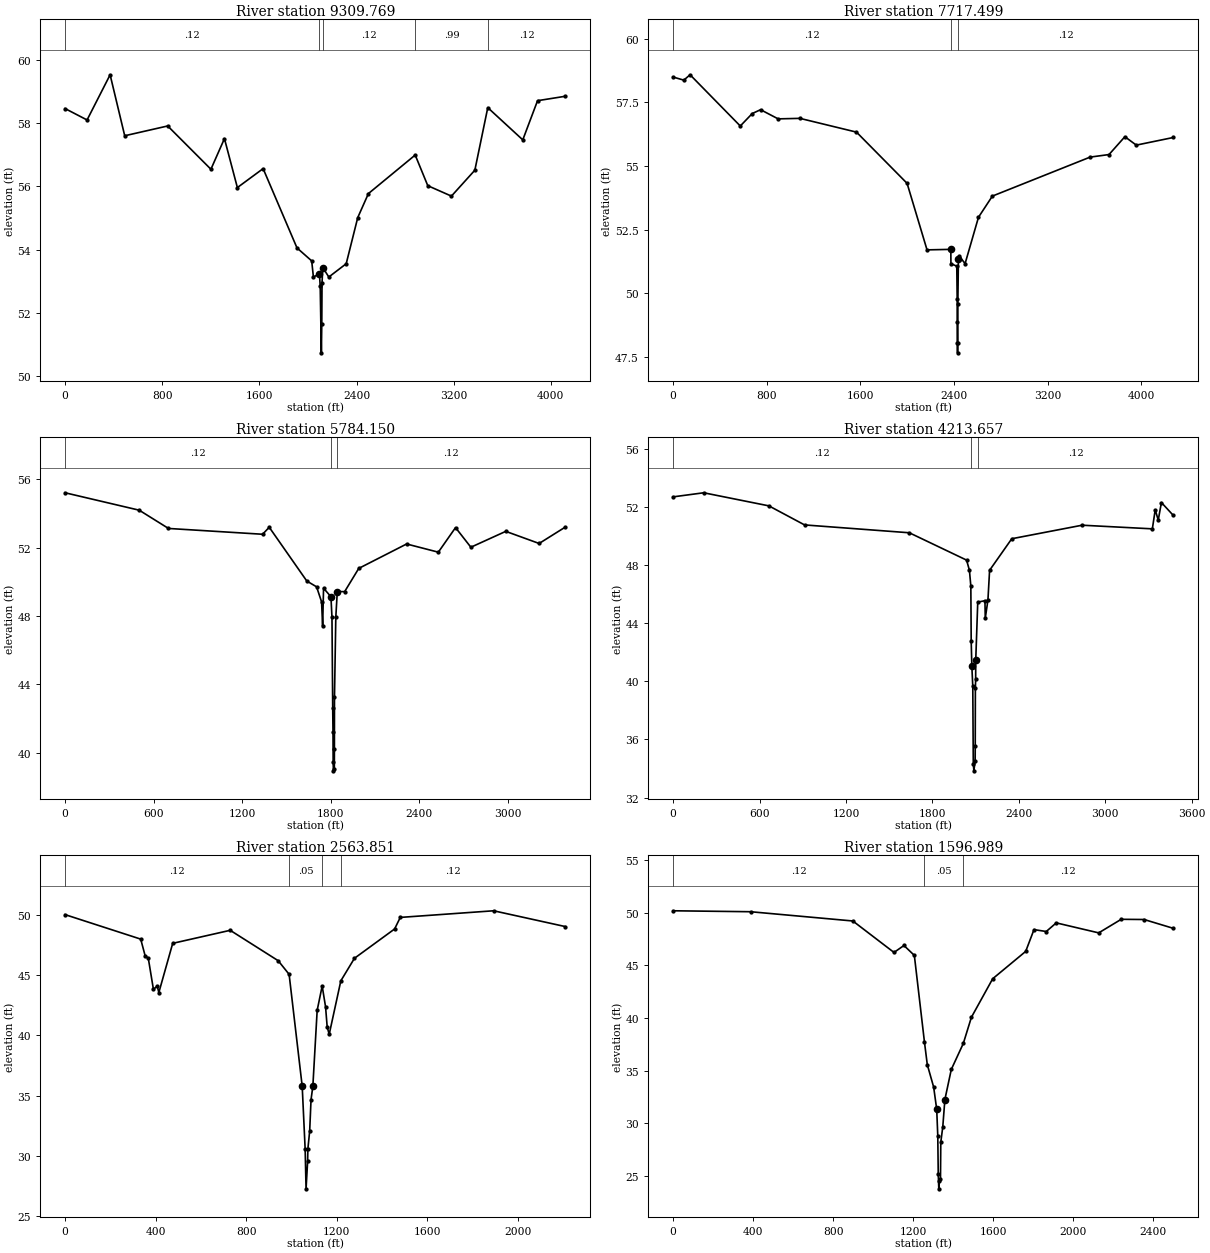
Type RM Length L Ch R = 1 ,9309.769,1590.06,1592.27,1592.97
BEGIN DESCRIPTION:
444v7
Bank Station offset =     2889.81
END DESCRIPTION:
XS GIS Cut Line= 4
     3200569.054    13910262.809     3199714.887    13908439.892
     3199668.654    13908352.418     3198798.221    13906544.059
#Sta/Elev= 30
       0   58.46  180.78    58.1  370.58   59.53  490.84    57.6  844.76   57.91
 1200.71   56.54 1312.09   57.51 1418.54   55.96 1630.61   56.56  1909.6   54.05
 2030.59   53.64 2044.69   53.13 2094.69   53.23 2100.69   52.83 2110.19   50.73
 2113.69   51.63 2115.69   52.93 2121.69   53.43 2171.69   53.13 2314.79   53.55
 2409.81   55.01 2497.68   55.77 2883.01   56.99 2986.63   56.02  3181.4   55.69
  3374.2   56.51 3480.64   58.49 3768.94   57.47 3890.54   58.71    4119   58.85
#Mann= 5 ,-1 , 0
       0     .12       0 2094.69     .05       0 2121.69     .12       0
 2883.01     .99       0 3480.64     .12       0
Bank Sta=2094.69,2121.69
XS Rating Curve= 0
Exp/Cntr=.3,.1

Type RM Length L Ch R = 1 ,7717.499,1932.32,1933.35,1920.83
BEGIN DESCRIPTION:
444v6
Bank Station offset =      2570.83
Low area in right overbank is blocked with "special ineffective" area n=0.99 - MAH 9/12/02
END DESCRIPTION:
XS GIS Cut Line= 4
     3202037.804    13909866.975     3201110.721    13907700.309
     3201087.995    13907630.814     3200308.637    13905960.725
#Sta/Elev= 30
       0   58.49   90.75   58.37   144.4   58.58  573.24   56.57  675.66   57.06
  746.59   57.21  896.73   56.85 1082.62   56.87 1565.96   56.33 1998.23   54.32
 2168.54   51.71  2371.8   51.73 2372.67   51.17 2422.67   51.07 2426.17   49.77
 2426.67   48.87 2427.67   48.07 2429.17   47.67 2430.67   48.07 2431.67   49.57
 2436.67   51.37 2443.67   51.47 2493.67   51.17 2608.07   52.99 2726.77   53.82
 3561.89   55.35 3723.16   55.45  3858.6   56.15 3956.16   55.82 4272.78   56.12
#Mann= 3 ,-1 , 0
       0     .12       0  2371.8     .05       0 2436.67     .12       0
Bank Sta=2371.8,2436.67
XS Rating Curve= 0
Exp/Cntr=.3,.1

Type RM Length L Ch R = 1 ,5784.150,1552.75,1570.49,1561.71
BEGIN DESCRIPTION:
444v5
Bank Station offset =      3181.82
3 points in left overbank deleted to eliminate low spot caused by discrepancy between surveyed section & LIDAR data. - MAH 9/12/02
Low area on ROB  is a small trib coming into the stream.   MAH 9/12/02
END DESCRIPTION:
XS GIS Cut Line= 6
     3203339.887    13908116.975     3203016.971    13907439.892
     3202780.897    13907004.271     3202621.244    13906674.223
     3202478.392    13906324.847     3201808.637    13905096.142
#Sta/Elev= 30
       0   55.22     502    54.2  700.51   53.13 1338.16   52.79 1383.12    53.2
 1637.68   50.05 1703.94   49.71 1737.78   48.83  1744.9   47.41 1751.18   49.63
 1801.18   49.13 1808.18   47.93 1813.18   42.63 1815.18   41.23 1816.18   39.43
 1818.18   38.93 1824.18   39.03 1824.68   40.23 1825.18   43.23 1834.18   47.93
 1844.18   49.43 1894.18   49.43 1989.71   50.79 2313.93   52.22 2528.89   51.74
 2645.42   53.18 2749.37   52.03 2985.83   52.96 3211.95   52.25 3389.12   53.21
#Mann= 3 ,-1 , 0
       0     .12       0 1801.18     .05       0 1844.18     .12       0
Bank Sta=1801.18,1844.18
XS Rating Curve= 0
Exp/Cntr=.3,.1

Type RM Length L Ch R = 1 ,4213.657,1643.55,1649.81,1647.26
BEGIN DESCRIPTION:
444v4
Bank Station offset =      2908
END DESCRIPTION:
XS GIS Cut Line= 4
     3204098.315    13908192.361     3203925.004    13906128.709
      3203918.09    13906040.833     3203806.453    13904731.722
#Sta/Elev= 30
       0   52.68  212.14   52.96  664.57   52.06   912.3   50.75 1639.66   50.21
 2037.23   48.33 2056.97   47.63 2066.78   46.54 2069.28   42.74 2073.78   41.04
 2080.28   39.64 2083.78   34.34 2087.78   33.84 2096.78   34.54 2097.28   35.54
 2098.28   39.54 2100.28   40.14 2100.78   41.44 2114.78   45.44 2164.78   45.54
 2166.89   44.33 2185.47   45.58    2197   47.63 2351.01    49.8 2839.54   50.73
 3327.07   50.48 3347.07   51.79 3368.02   51.08 3389.98   52.29 3472.93    51.4
#Mann= 3 ,-1 , 0
       0     .12       0 2066.78     .05       0 2114.78     .12       0
Bank Sta=2073.78,2100.78
XS Rating Curve= 0
Exp/Cntr=.3,.1

Type RM Length L Ch R = 1 ,2563.851,943.93,966.86,930.35
BEGIN DESCRIPTION:
444v3
Bank Station offset =      3936
Low areas in right overbank blocked with "special ineffective" area n=0.99 - MAH 9/12/02
END DESCRIPTION:
XS GIS Cut Line= 4
     3205060.205    13907345.751     3205428.259    13906394.076
     3205451.367    13906335.881     3205852.139    13905283.535
#Sta/Elev= 30
       0   50.02  333.88   47.99  353.41   46.61   367.5   46.39  389.97   43.83
   406.9   44.09  413.94   43.56  475.18   47.64  729.14   48.72  941.07    46.2
  989.32   45.07 1047.14   35.78 1060.14   30.58 1064.14   27.28 1071.14   29.58
 1072.14   30.58 1080.14   32.08 1086.14   34.68 1094.14   35.78 1113.19   42.08
 1135.32    44.1 1150.24   42.38 1157.38   40.72 1166.29   40.09 1217.72   44.53
 1277.88    46.4  1455.2   48.83 1480.26   49.79 1892.53   50.34 2209.06   49.03
#Mann= 4 ,-1 , 0
       0     .12       0  989.32     .05       0 1135.32     .99       0
 1217.72     .12       0
Bank Sta=1047.14,1094.14
XS Rating Curve= 0
Exp/Cntr=.3,.1

Type RM Length L Ch R = 1 ,1596.989,292.21,306.09,308.76
BEGIN DESCRIPTION:
444v2
Bank Station offset =      3672
END DESCRIPTION:
XS GIS Cut Line= 6
     3206351.365    13907762.851     3206361.105    13906895.992
     3206333.416    13906467.255     3206312.557    13906399.334
     3206009.413    13905591.228     3205981.246    13905322.984
#Sta/Elev= 30
       0   50.19   386.9    50.1   898.1   49.22 1103.89   46.23 1153.67   46.89
 1205.58   45.95 1255.99   37.74 1270.37   35.56 1302.15   33.43 1317.39   31.32
 1322.72   28.82  1325.1    25.2 1327.89   23.76 1329.69   24.47 1336.28   24.71
 1337.81   28.19 1347.77   29.66 1358.28   32.25 1390.35   35.11 1450.39   37.58
 1490.89   40.07 1597.29   43.73 1762.26   46.33  1803.7    48.4 1865.09   48.22
 1915.01   49.04 2127.24   48.09 2239.73   49.38 2354.22   49.36 2500.41   48.52
#Mann= 3 ,-1 , 0
       0     .12       0 1255.99     .05       0 1450.39     .12       0
Bank Sta=1317.39,1358.28
XS Rating Curve= 0
Exp/Cntr=.3,.1

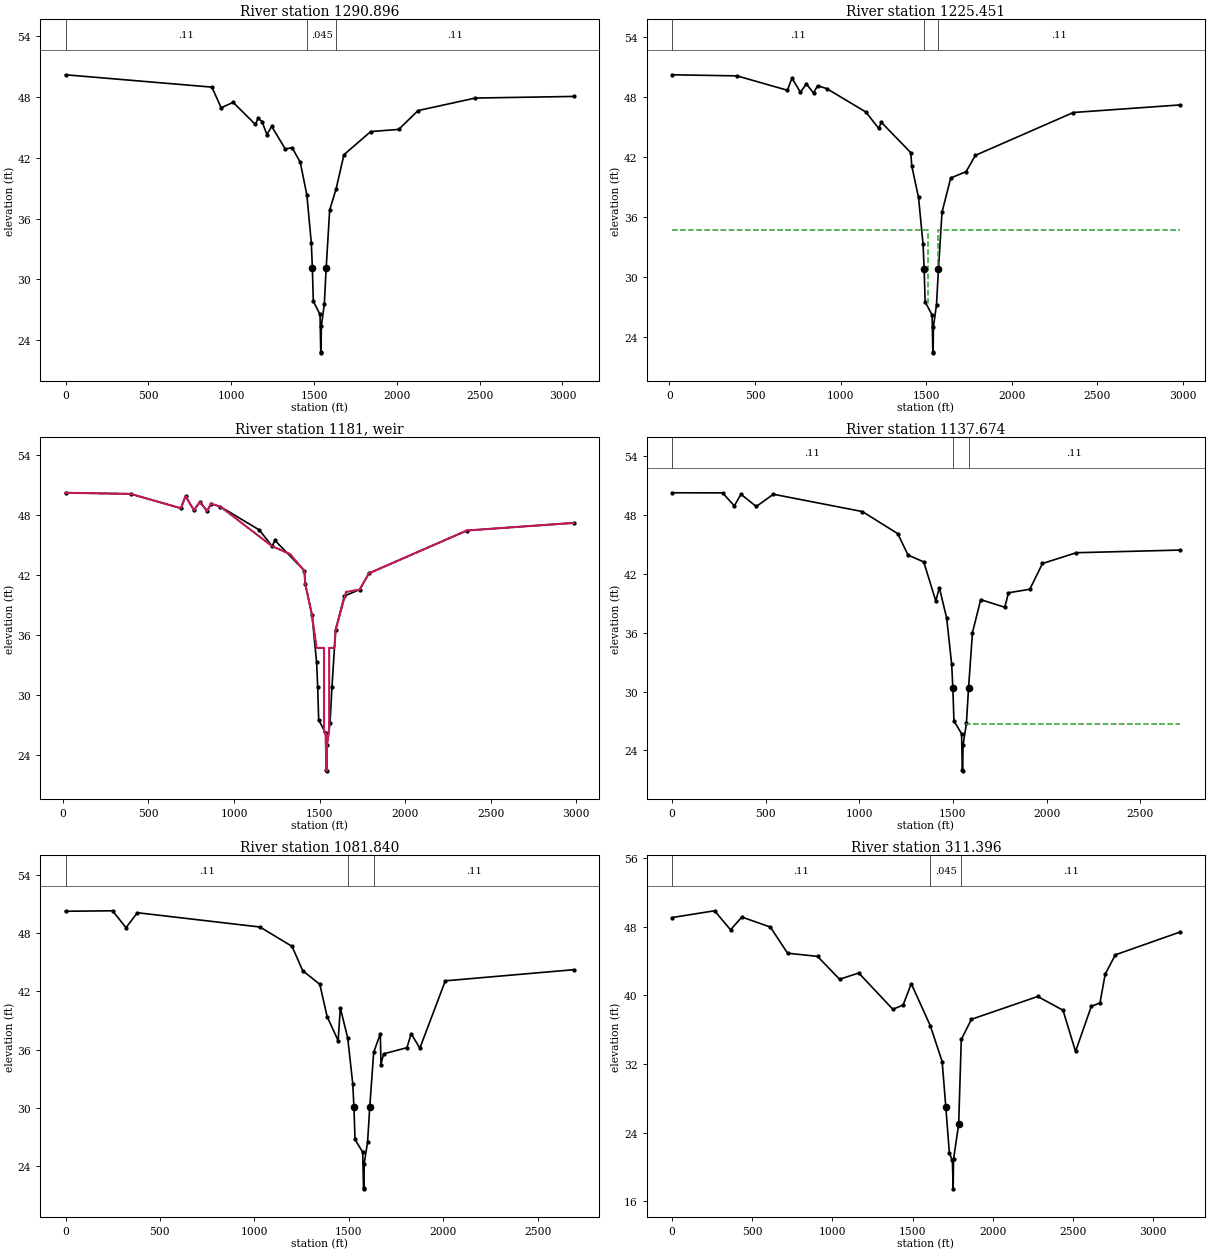
Type RM Length L Ch R = 1 ,1290.896,61.64,65.44,75.36
BEGIN DESCRIPTION:
444s1u - bridge XS 4/4 (Golf Club Drive)
Bank Station offset =      3458
END DESCRIPTION:
XS GIS Cut Line= 4
     3206392.032    13907763.123     3206552.031    13906347.892
     3206523.781    13906149.635      3206699.99    13904717.766
#Sta/Elev= 30
       0   50.21  883.98   48.99  939.53   46.95 1012.19   47.48 1146.45    45.3
 1163.14   45.92 1186.89   45.58 1215.86    44.3 1244.94   45.11 1326.69   42.87
 1368.02   43.01  1417.3   41.56 1457.32   38.31 1483.98   33.59 1490.23   31.16
 1496.04   27.83 1536.66   26.52 1540.91   22.86 1542.46   22.73 1544.61   25.34
 1562.56   27.57 1573.88   31.16 1594.84   36.84 1633.91   38.94 1680.93   42.31
 1842.85    44.6  2011.6   44.81 2128.25   46.67 2473.67   47.91 3067.18   48.07
#Mann= 3 ,-1 , 0
       0     .11       0 1457.32    .045       0 1633.91     .11       0
Bank Sta=1490.23,1573.88
XS Rating Curve= 0
Exp/Cntr=.5,.3

Type RM Length L Ch R = 1 ,1225.451,78.53,87.78,85.31
BEGIN DESCRIPTION:
copy of 444s1u - bridge XS 3/4 (Golf Club Drive)
Surveyed channel section adjusted (-0.35 ft)
Ineffective flow areas set based on contraction to vertical bridge walls beneath road.
The n values at XS 2/4, 3/4 and internal bridge sections were set to 0.035 based on observed maintained grassy areas at bridge approaches and concrete vertical sidewalls beneath road at bridge.
Bank Station offset =      3474
END DESCRIPTION:
XS GIS Cut Line= 4
     3206437.656    13907746.015     3206582.663    13906348.921
     3206616.895    13906126.913     3206888.186    13904814.716
#Sta/Elev= 30
   15.06   50.24  395.07   50.13   689.6   48.69  716.37   49.91  765.71   48.49
   800.5   49.33  842.28   48.41  866.26   49.15  920.23   48.85 1148.11   46.51
 1222.18   44.89 1239.59   45.46 1410.57   42.44 1416.73   41.08 1455.94   37.96
  1482.6   33.24 1488.85   30.81 1494.66   27.48 1535.28   26.17 1539.53   22.51
 1541.08   22.38 1543.23   24.99 1561.18   27.22  1572.5   30.81 1593.46   36.49
 1644.29    39.9  1734.1   40.54 1788.52   42.17 2360.84   46.46 2984.24   47.22
#Mann= 3 ,-1 , 0
   15.06     .11       0 1488.85    .035       0  1572.5     .11       0
#XS Ineff= 2 , 0
       0    1509    34.7    1571       0    34.7
Permanent Ineff=
       F       F
Bank Sta=1488.85,1572.5
XS Rating Curve= 0
Exp/Cntr=.5,.3

Type RM Length L Ch R = 5 ,1181    ,,,
BEGIN DESCRIPTION:
Inline Weir, beneath Golf Club Drive; 444s1
END DESCRIPTION:
IW Pilot Flow=0
#Inline Weir SE= 30
   15.06   50.24  395.07   50.13   689.6   48.69  716.37   49.91  765.71   48.49
   800.5   49.33  842.28   48.41  866.26   49.15  920.23   48.85 1222.18   44.89
 1327.13    44.1 1410.57   42.44 1416.73   41.08 1455.94   37.96  1482.6    34.7
 1525.99    34.7    1526   26.24 1535.28   26.17 1539.53   22.51 1541.08   22.38
 1543.23   24.99    1556    26.5 1556.01    34.7    1587    34.7 1593.46   36.49
 1654.68    40.3  1734.1   40.54 1788.52   42.17 2360.84   46.46 2984.24   47.22
IW Dist,WD,Coef,Skew,MaxSub,Min_El,Is_Ogee,SpillHt,DesHd
27.89,32,3,0,.95,, 0 ,,,0,0,

Type RM Length L Ch R = 1 ,1137.674,55.83,55.83,65.48
BEGIN DESCRIPTION:
copy of 444s1u - bridge XS 2/4 (Golf Club Drive)
Surveyed channel section adjusted (-0.83 ft).
Ineffective flow areas set based on expansion from end of vertical sidewalls under road.
The n values at XS 2/4, 3/4 and internal bridge sections were set to 0.035 based on observed maintained grassy areas at bridge approaches and concrete vertical sidewalls beneath road at bridge.
Bank Station offset =      3448
END DESCRIPTION:
XS GIS Cut Line= 4
       3206523.2    13907734.609     3206658.274    13906309.697
     3206693.105    13906083.806     3207036.462    13905088.456
#Sta/Elev= 30
       0   50.29  270.28   50.28  333.03   48.95  368.22   50.14  450.16   48.89
  541.38   50.14 1017.13   48.37  1205.9   46.11 1260.57   43.93 1344.52   43.23
 1408.68   39.24 1427.73    40.6 1466.94   37.48  1493.6   32.76 1499.85   30.33
 1505.66      27 1546.28   25.69 1550.53   22.03 1552.08    21.9 1554.23   24.51
 1572.18   26.74  1583.5   30.33 1604.46   36.01  1648.5   39.38 1777.04    38.6
 1796.79   40.08 1910.82   40.44 1978.41   43.07 2159.14   44.17 2712.77   44.44
#Mann= 3 ,-1 , 0
       0     .11       0 1499.85    .035       0  1583.5     .11       0
#XS Ineff= 2 , 0
       0    1509    26.7    1571       0    26.7
Permanent Ineff=
       F       F
Bank Sta=1499.85,1583.5
XS Rating Curve= 0
Exp/Cntr=.5,.3

Type RM Length L Ch R = 1 ,1081.840,753.51,770.44,741.76
BEGIN DESCRIPTION:
copy of 444s1u - bridge XS 1/4 (Golf Club Drive)
Surveyed channel section adjusted (-1.13 ft)
MAH 9/13/02
Bank Station offset =      3420
END DESCRIPTION:
XS GIS Cut Line= 4
     3206546.011    13907746.015     3206712.751    13906298.206
     3206747.582    13906072.315     3207059.274     13905116.97
#Sta/Elev= 30
       0   50.29  248.96   50.34  320.62   48.59  380.48   50.14 1030.36   48.66
 1199.97   46.66 1256.23   44.15 1346.83   42.74 1385.76    39.4 1444.05   36.91
 1455.59    40.3  1494.8   37.18 1521.46   32.46 1527.71   30.03 1533.52    26.7
 1574.14   25.39 1578.39   21.73 1579.94    21.6 1582.09   24.21 1600.04   26.44
 1611.36   30.03 1632.32   35.71 1667.42   37.63 1670.85   34.45 1684.74   35.55
 1808.33   36.19 1830.82   37.63 1876.81   36.14 2011.66    43.1 2690.85   44.25
#Mann= 3 ,-1 , 0
       0     .11       0  1494.8    .045       0 1632.32     .11       0
Bank Sta=1527.71,1611.36
XS Rating Curve= 0
Exp/Cntr=.3,.1

Type RM Length L Ch R = 1 ,311.396 ,306.5,311.4,296.02
BEGIN DESCRIPTION:
444v1
Bank Station offset =      3248
END DESCRIPTION:
XS GIS Cut Line= 5
     3207338.721    13907646.237     3207402.186    13905979.164
     3207368.127    13905839.155     3207203.685    13905155.687
     3206848.327    13904609.959
#Sta/Elev= 30
       0   49.08  265.38   49.87  365.03   47.65  435.72   49.14  613.08   47.97
  720.82   44.92  907.28   44.55 1044.69   41.88 1164.05   42.61 1376.82   38.38
 1440.48   38.87 1491.63   41.36 1610.21   36.46 1684.11   32.27 1707.03   26.94
 1729.02   21.59 1747.95   20.74 1752.46   17.43 1754.97   20.88 1786.92   24.96
 1803.29   34.86 1866.53   37.21 2279.46   39.87 2437.19   38.27 2515.34   33.46
 2613.98   38.73 2667.68   39.11  2700.1   42.47 2763.41   44.73 3166.57   47.39
#Mann= 3 ,-1 , 0
       0     .11       0 1610.21    .045       0 1803.29     .11       0
Bank Sta=1707.03,1786.92
XS Rating Curve= 0
Exp/Cntr=.3,.1

Chan Stop Cuts=-1